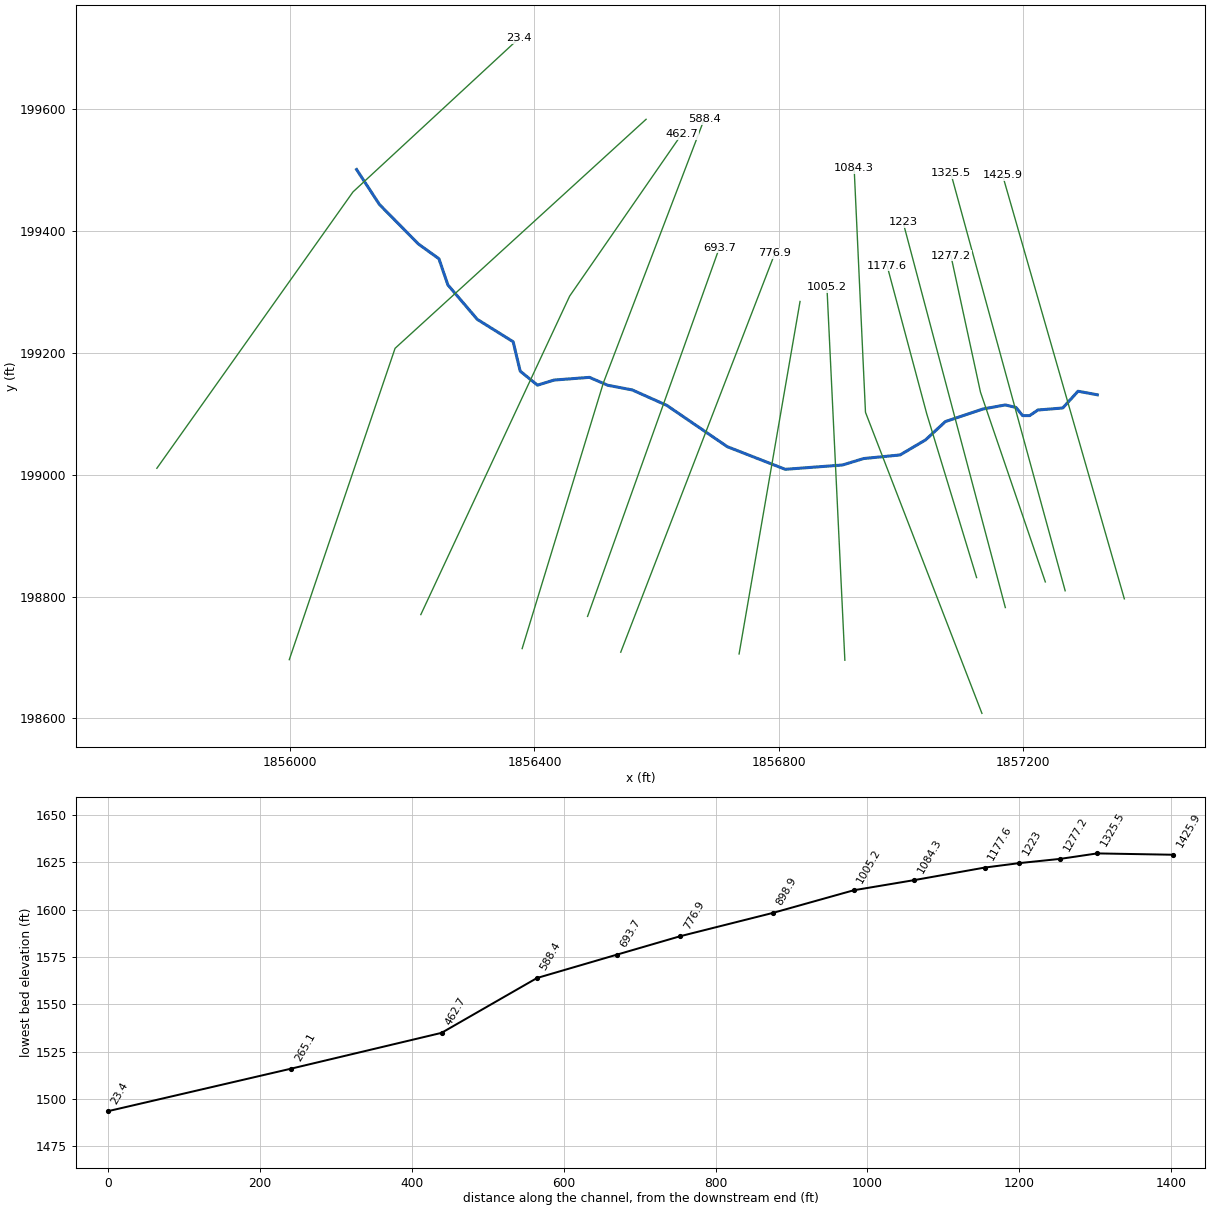
--- HickoryBr2.prj (project) ---

Proj Title=HickoryBr2
Current Plan=p01
Default Exp/Contr=0,0
English Units
Geom File=g01
Flow File=f01
Plan File=p01
BEGIN DESCRIPTION:
END DESCRIPTION:
DSS Export Rating Curves= 0
DSS Export Rating Curve Sorted= 0
DSS Export Volume Flow Curves= 0
DXF OffsetX= 0
DXF OffsetY= 0
DXF ScaleX= 0
DXF ScaleY= 0

--- HickoryBr2.p01 (plan) ---

Plan Title=Floodplain
Program Version=4.00
Geom File=g01
Flow File=f01
K Sum by GR=0
Std Step Tol=0.01
Critical Tol=0.01
Num of Std Step Trials=20
Max Error Tol=0.3
Flow Tol Ratio=0.001
Split Flow NTrial=30
Split Flow Tol=0.02
Split Flow Ratio=0.02
Log Output Level=0
Friction Slope Method=1
Unsteady Friction Slope Method=2
Unsteady Bridges Friction Slope Method=1
Global Log Level=0
CheckData=False
Run HTab=0
Run UNet=0
Run PostProcess=0
UNET Theta=0
UNET Theta Warmup=0
UNET ZTol=0
UNET ZSATol=0
UNET MxIter=0
UNET MaxInSteps=0
UNET DtIC=0
UNET DtMin=0
UNET MaxCRTS=0
UNET WFStab=0
UNET SFStab=0
UNET WFX=0
UNET SFX=0
UNET DSS MLevel=0
UNET DZMax Abort=0
UNET Convert EG Bridges=0
UNET Use Existing IB Tables=0
UNET Froude Limit=0
UNET Froude Power=0
Write IC File=0
Echo Input=False
Echo Output=False
Write Detailed=0

--- HickoryBr2.f01 (steady flow) ---

Flow Title=NFF Regression Equation
Program Version=4.00
Number of Profiles=1
Profile Names=P100yr
River Rch & RM=HickoryBr2,Main      ,1425.9
515.3078
River Rch & RM=HickoryBr2,Main      ,265.1
548.7863
Boundary for River Rch & Prof#=HickoryBr2,Main      ,1
Up Type=0
Dn Type=3
Dn Slope=0.138612

--- HickoryBr2.g01 (geometry) ---

Geom Title=USGS 10m DEM
Program Version=4.00

River Reach=HickoryBr2     ,Main
Reach XY= 30
     1857322.392      199131.289     1857290.725      199137.122
     1857265.724      199109.621     1857224.889      199106.288
     1857211.556      199097.121     1857199.888      199097.121
     1857189.055      199110.455     1857171.554      199114.622
     1857134.886      199107.955     1857073.399      199087.351
     1857040.957      199057.268     1856999.077      199032.494
     1856939.502      199026.596     1856904.701      199015.979
     1856810.915      199008.900     1856715.949      199046.061
     1856616.854      199113.894     1856560.228      199139.258
     1856520.118      199146.926     1856490.036      199159.902
     1856432.132      199155.478     1856404.868      199147.089
     1856376.555      199170.159     1856365.020      199218.396
     1856306.297      199255.098     1856258.060      199311.724
     1856243.380      199354.717     1856209.824      199378.836
     1856145.858      199443.850     1856108.421      199501.254

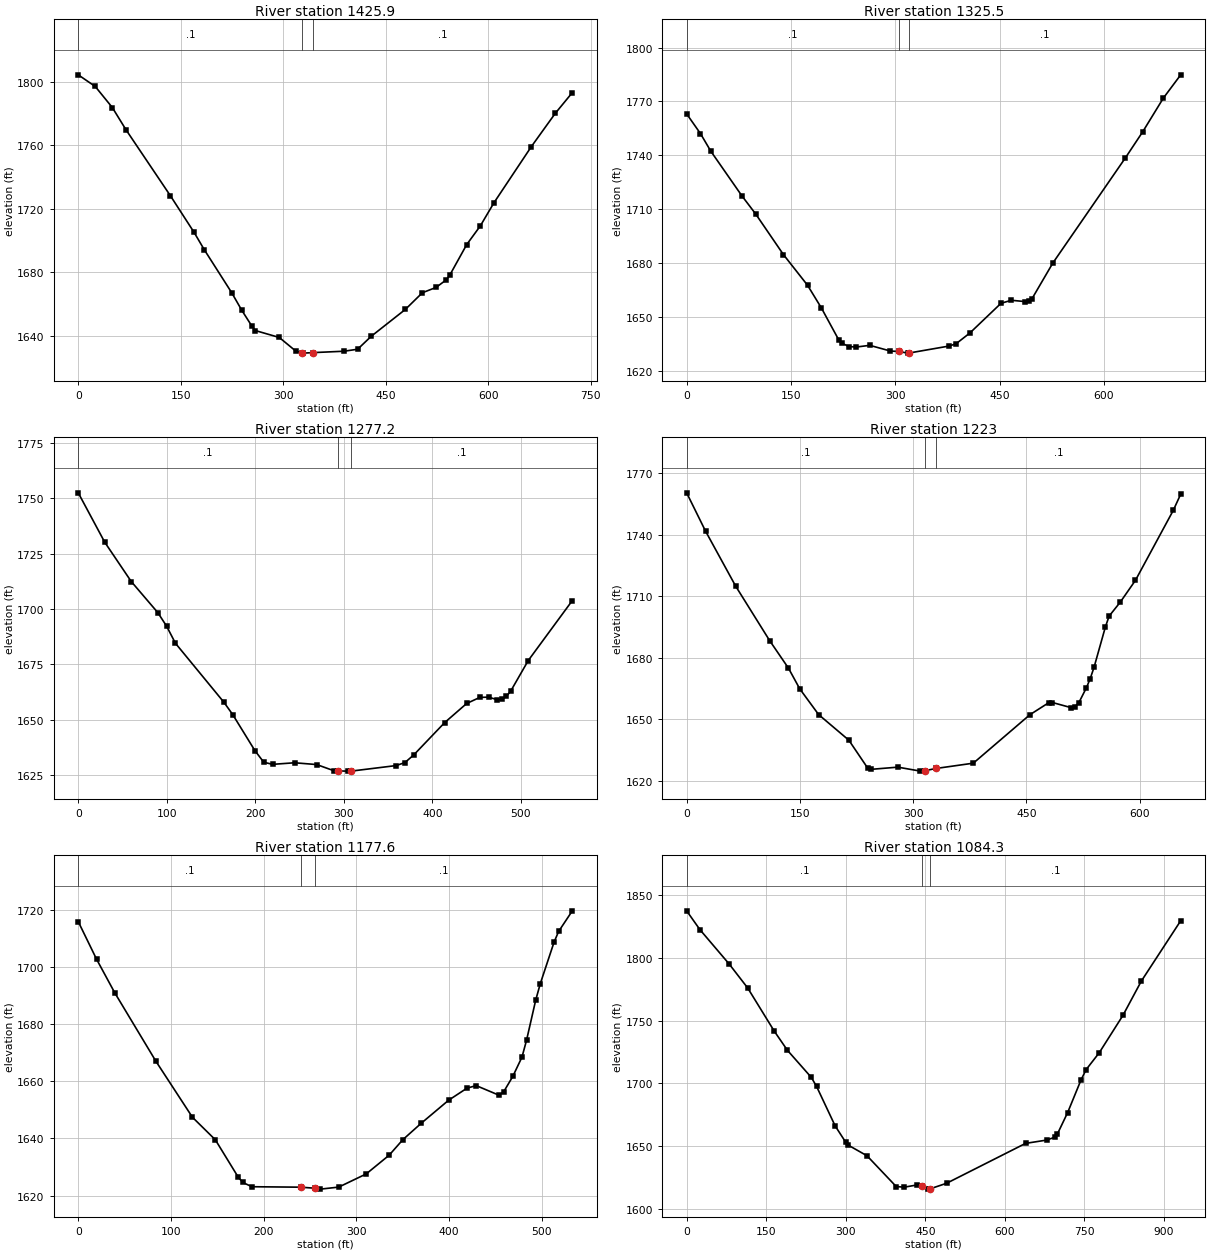
Type RM Length L Ch R = 1 ,1425.9,90.3,100.4,98.4
XS GIS Cut Line= 2
     1857366.619      198796.219     1857167.187      199491.476
#Sta/Elev= 30
       0 1804.21    24.9 1796.87    49.9 1783.62    69.8 1769.70   134.7 1728.24
   169.6 1705.04   184.6 1694.08   224.5 1667.19   239.4 1656.02   254.4 1645.91
   259.4 1643.24   294.3 1638.91   319.2 1630.08   328.2 1629.11   329.2 1629.05
   343.2 1629.36   389.1 1630.25   409.0 1631.50   429.0 1639.68   478.9 1656.57
   503.8 1667.06   523.8 1670.40   538.7 1675.14   543.7 1677.98   568.7 1697.38
   588.6 1709.11   608.6 1723.70   663.4 1759.08   698.4 1780.00   723.3 1793.02
#Mann= 3 , 0 , 0
       0     0.1       0   328.2   0.045       0   343.2     0.1       0
Bank Sta=   328.2,   343.2
Exp/Cntr=0.3,0.1

Type RM Length L Ch R = 1 ,1325.5,57.9,48.3,48.7
XS GIS Cut Line= 2
     1857269.658      198809.441     1857082.346      199494.782
#Sta/Elev= 30
       0 1763.10    19.9 1752.09    34.8 1742.27    79.5 1717.39    99.4 1707.24
   139.1 1684.72   173.9 1667.57   193.8 1654.92   218.6 1637.24   223.6 1635.19
   233.5 1633.45   243.4 1633.13   263.3 1634.10   293.1 1630.92     305 1630.68
   318.0 1629.76     320 1629.83   377.6 1633.72   387.5 1634.99   407.4 1641.01
   452.1 1657.54   467.0 1659.21   486.9 1658.48   491.9 1658.79   496.8 1660.18
   526.6 1679.96   631.0 1738.61   655.8 1753.07   685.6 1771.92   710.5 1784.85
#Mann= 3 , 0 , 0
       0     0.1       0     305   0.045       0     320     0.1       0
Bank Sta=     305,     320
Exp/Cntr=0.3,0.1

Type RM Length L Ch R = 1 ,1277.2,56,54.3,52.5
XS GIS Cut Line= 3
     1857237.129      198823.981     1857130.847      199135.690
     1857082.465      199359.358
#Sta/Elev= 30
       0 1752.44    29.9 1730.18    59.9 1712.42    89.8 1698.45    99.8 1692.31
   109.8 1684.58   164.7 1657.89   174.6 1652.36   199.6 1636.14   209.6 1630.90
   219.6 1629.95   244.5 1630.66   269.4 1629.85   289.4 1626.99   293.6 1626.97
   304.4 1626.89   308.6 1626.91   359.2 1629.40   369.1 1630.76   379.1 1634.22
   413.9 1648.75   438.8 1657.40   453.7 1660.15   463.6 1660.27   473.6 1659.08
   478.6 1659.23   483.6 1660.57   488.5 1662.93   508.4 1676.78   558.2 1703.84
#Mann= 3 , 0 , 0
       0     0.1       0   293.6   0.045       0   308.6     0.1       0
Bank Sta=   293.6,   308.6
Exp/Cntr=0.3,0.1

Type RM Length L Ch R = 1 ,1223,45.3,45.4,45.6
XS GIS Cut Line= 2
     1857171.595      198781.895     1857004.116      199414.348
#Sta/Elev= 30
       0 1760.42    25.0 1741.75    64.9 1714.90   109.9 1688.32   134.8 1674.88
   149.8 1664.77   174.8 1652.21   214.8 1639.72   239.7 1626.13   244.7 1625.52
   279.7 1626.57   309.6 1624.63   315.6 1624.86   330.6 1625.95   379.6 1628.51
   454.5 1652.15   479.4 1658.00   484.4 1658.10   509.4 1655.57   514.4 1656.14
   519.4 1658.09   529.4 1665.36   534.4 1669.80   539.4 1675.23   554.4 1694.90
   559.4 1700.27   574.3 1707.15   594.3 1717.75   644.3 1751.83   654.2 1759.78
#Mann= 3 , 0 , 0
       0     0.1       0   315.6   0.045       0   330.6     0.1       0
Bank Sta=   315.6,   330.6
Exp/Cntr=0.3,0.1

Type RM Length L Ch R = 1 ,1177.6,91,93.3,95.6
XS GIS Cut Line= 3
     1857124.501      198831.120     1857042.807      199099.998
     1856977.769      199343.495
#Sta/Elev= 30
       0 1715.77    19.7 1702.67    39.4 1690.89    83.8 1666.96   123.2 1647.39
   147.9 1639.52   172.6 1626.46   177.5 1624.62   187.3 1623.12   240.1 1622.96
   255.1 1622.60   261.3 1622.28   281.0 1622.99   310.7 1627.60   335.4 1634.14
   350.2 1639.57   370.0 1645.30   399.6 1653.36   419.4 1657.57   429.3 1658.46
   454.0 1655.09   458.9 1656.27   468.8 1661.68   478.7 1668.43   483.6 1674.28
   493.5 1688.33   498.5 1694.14   513.3 1708.59   518.2 1712.32   533.0 1719.54
#Mann= 3 , 0 , 0
       0     0.1       0   240.1   0.045       0   255.1     0.1       0
Bank Sta=   240.1,   255.1
Exp/Cntr=0.3,0.1

Type RM Length L Ch R = 1 ,1084.3,86.5,79.1,71.7
XS GIS Cut Line= 3
     1857133.240      198608.133     1856942.413      199102.529
     1856923.827      199503.554
#Sta/Elev= 30
       0 1837.57    25.0 1822.59    80.0 1795.24   115.0 1776.10   165.0 1741.74
   190.0 1726.33   235.0 1704.75   245.0 1697.47   280.0 1666.02   300.0 1652.94
   305.0 1650.61   340.0 1642.23   395.0 1617.71   410.0 1617.16   435.0 1619.00
   444.1 1617.95   455.0 1615.62   459.1 1615.88   490.0 1620.28   639.0 1652.11
   678.6 1654.73   693.5 1656.94   698.5 1659.19   718.3 1676.72   743.1 1702.34
   753.0 1710.90   777.8 1724.38   822.4 1754.12   857.1 1781.49   931.4 1829.66
#Mann= 3 , 0 , 0
       0     0.1       0   444.1   0.045       0   459.1     0.1       0
Bank Sta=   444.1,   459.1
Exp/Cntr=0.3,0.1

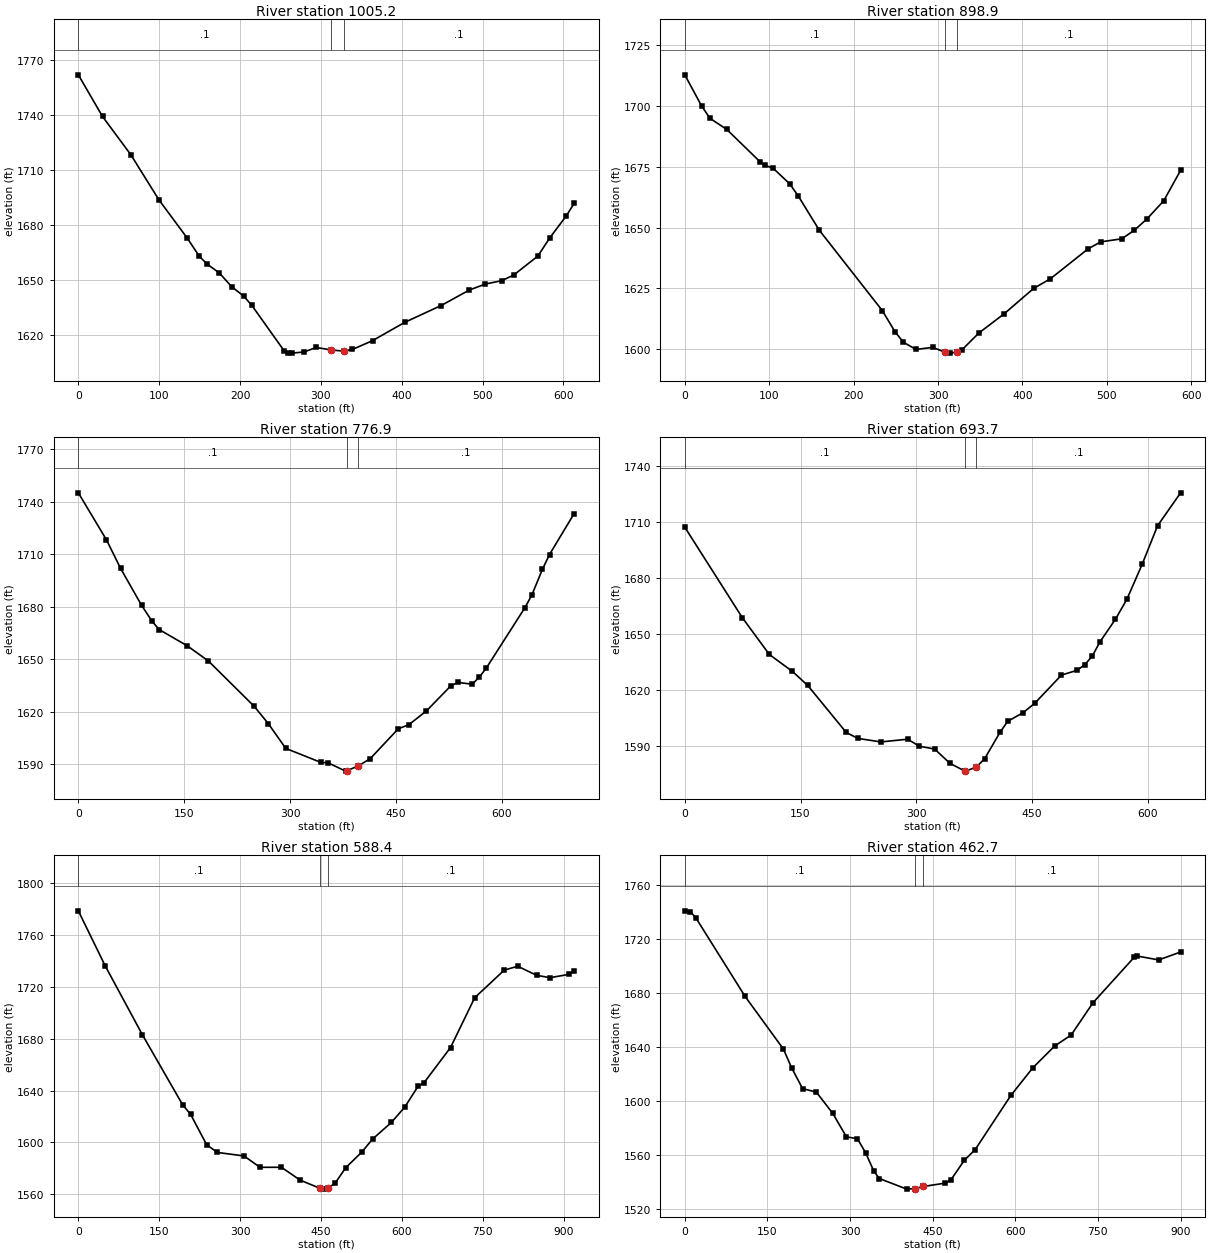
Type RM Length L Ch R = 1 ,1005.2,111.2,106.3,101.3
XS GIS Cut Line= 2
     1856908.623      198695.401     1856879.241      199308.021
#Sta/Elev= 30
       0 1762.07    29.9 1739.36    64.8 1718.58    99.7 1693.89   134.6 1673.09
   149.6 1663.15   159.6 1658.74   174.5 1654.00   189.5 1646.59   204.4 1641.44
   214.4 1636.46   254.3 1611.73   259.3 1610.32   264.3 1610.30   279.2 1610.93
   294.2 1613.39     313 1612.02     328 1611.39   339.1 1612.32   364.0 1617.13
   403.9 1627.12   448.8 1636.27   483.7 1644.72   503.6 1648.00   523.6 1649.79
   538.5 1652.88   568.4 1663.23   583.4 1673.33   603.4 1685.02   613.3 1691.99
#Mann= 3 , 0 , 0
       0     0.1       0     313   0.045       0     328     0.1       0
Bank Sta=     313,     328
Exp/Cntr=0.3,0.1

Type RM Length L Ch R = 1 ,898.9,126.4,122,117.5
XS GIS Cut Line= 2
     1856735.268      198705.685     1856835.168      199284.515
#Sta/Elev= 30
       0 1712.78    19.9 1699.97    29.9 1694.88    49.8 1690.31    89.6 1676.88
    94.6 1675.59   104.5 1674.43   124.4 1667.92   134.4 1662.96   159.3 1648.90
   234.0 1615.82   248.9 1607.22   258.8 1602.88   273.8 1599.86   293.7 1600.72
   307.7 1598.81   313.6 1598.35   322.7 1598.76   328.5 1599.75   348.4 1606.62
   378.3 1614.51   413.2 1624.94   433.1 1628.91   477.9 1641.26   492.8 1644.10
   517.7 1645.35   532.6 1648.89   547.6 1653.56   567.5 1661.04   587.4 1673.54
#Mann= 3 , 0 , 0
       0     0.1       0   307.7   0.045       0   322.7     0.1       0
Bank Sta=   307.7,   322.7
Exp/Cntr=0.3,0.1

Type RM Length L Ch R = 1 ,776.9,82.7,83.3,83.8
XS GIS Cut Line= 2
     1856541.346      198708.623     1856794.033      199363.847
#Sta/Elev= 30
       0 1745.07    39.8 1718.24    59.8 1701.94    89.6 1680.77   104.6 1671.59
   114.6 1666.91   154.4 1657.62   184.3 1648.95   249.0 1623.11   269.0 1613.22
   293.8 1599.04   343.7 1590.99   353.6 1590.84   378.5 1586.04     381 1586.38
     396 1588.91   413.4 1593.14   453.2 1610.25   468.2 1612.57   493.1 1620.47
   527.9 1634.89   537.9 1636.73   557.8 1635.70   567.8 1639.69   577.8 1644.88
   632.5 1679.40   642.5 1686.78   657.4 1701.43   667.4 1709.82   702.3 1733.24
#Mann= 3 , 0 , 0
       0     0.1       0     381   0.045       0     396     0.1       0
Bank Sta=     381,     396
Exp/Cntr=0.3,0.1

Type RM Length L Ch R = 1 ,693.7,104.3,105.3,104.8
XS GIS Cut Line= 2
     1856486.988      198767.387     1856702.948      199372.662
#Sta/Elev= 30
       0 1707.20    74.7 1658.56   109.6 1638.90   139.5 1629.81   159.4 1622.26
   209.2 1597.07   224.2 1593.87   254.1 1591.98   288.9 1593.45   303.9 1589.68
   323.8 1588.16   343.7 1580.47   362.8 1576.39   363.7 1576.31   377.8 1578.45
   388.6 1582.97   408.5 1597.13   418.5 1603.03   438.4 1607.68   453.3 1612.62
   488.2 1627.85   508.1 1630.37   518.1 1633.30   528.1 1638.05   538.0 1645.64
   558.0 1657.74   572.9 1668.48   592.8 1687.36   612.8 1708.06   642.6 1725.65
#Mann= 3 , 0 , 0
       0     0.1       0   362.8   0.045       0   377.8     0.1       0
Bank Sta=   362.8,   377.8
Exp/Cntr=0.3,0.1

Type RM Length L Ch R = 1 ,588.4,130.2,125.7,122.2
XS GIS Cut Line= 3
     1856379.786      198714.514     1856512.813      199150.676
     1856678.186      199583.910
#Sta/Elev= 30
       0 1778.54    49.6 1736.30   119.0 1682.86   193.3 1629.12   208.2 1621.66
   237.9 1598.26   257.7 1592.26   307.3 1589.54   337.0 1580.77   376.7 1580.81
   411.4 1570.89   447.9 1564.66   456.0 1563.96   462.9 1564.84   475.9 1568.30
   495.9 1580.44   525.8 1592.53   545.8 1602.57   580.6 1615.34   605.6 1627.27
   630.5 1643.49   640.5 1645.61   690.4 1673.15   735.2 1711.54   790.1 1732.86
   815.0 1735.80   849.9 1728.86   874.8 1726.96   909.8 1729.54   919.7 1731.86
#Mann= 3 , 0 , 0
       0     0.1       0   447.9   0.045       0   462.9     0.1       0
Bank Sta=   447.9,   462.9
Exp/Cntr=0.3,0.1

Type RM Length L Ch R = 1 ,462.7,206.7,197.6,188.5
XS GIS Cut Line= 3
     1856213.734      198770.326     1856457.606      199293.330
     1856641.245      199559.239
#Sta/Elev= 30
       0 1740.86    10.0 1740.30    19.9 1735.78   109.4 1677.58   179.1 1638.55
   194.0 1624.68   213.9 1609.32   238.8 1606.76   268.6 1591.04   293.5 1573.64
   313.4 1572.28   328.3 1561.86   343.3 1548.23   353.2 1542.83   403.0 1534.99
   418.3 1535.43   433.3 1536.95   472.6 1539.43   482.6 1541.51   507.4 1556.27
   527.3 1564.29   592.0 1604.31   631.8 1624.71   671.5 1640.84   701.4 1648.98
   741.1 1672.86   815.7 1706.42   820.7 1707.47   860.4 1704.54   900.2 1710.41
#Mann= 3 , 0 , 0
       0     0.1       0   418.3   0.045       0   433.3     0.1       0
Bank Sta=   418.3,   433.3
Exp/Cntr=0.3,0.1

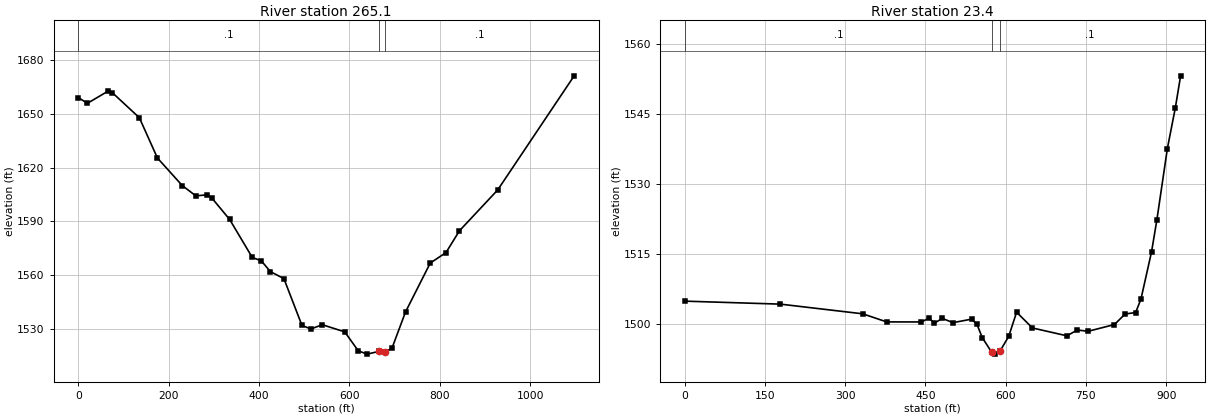
Type RM Length L Ch R = 1 ,265.1,241.1,241.7,242.3
XS GIS Cut Line= 3
     1855998.158      198696.337     1856171.513      199207.588
     1856582.864      199583.680
#Sta/Elev= 30
       0 1658.95    20.0 1655.74    65.0 1662.41    75.0 1661.72   135.0 1647.74
   175.0 1625.31   229.9 1609.98   259.9 1604.25   284.9 1604.78   294.9 1603.19
   334.9 1591.07   384.9 1569.94   404.9 1568.06   424.9 1562.07   454.9 1558.16
   494.9 1532.07   514.8 1530.13   539.8 1532.50   589.6 1528.50   619.5 1517.93
   639.4 1516.12   664.5 1517.62   679.5 1517.40   694.1 1519.44   724.0 1539.59
   778.7 1566.80   813.6 1572.66   843.4 1584.80   928.0 1607.52  1097.2 1671.05
#Mann= 3 , 0 , 0
       0     0.1       0   664.5   0.045       0   679.5     0.1       0
Bank Sta=   664.5,   679.5
Exp/Cntr=0.3,0.1

Type RM Length L Ch R = 1 ,23.4,27.2,23.4,19.5
XS GIS Cut Line= 3
     1855781.166      199010.592     1856102.552      199464.407
     1856374.607      199716.623
#Sta/Elev= 30
       0 1504.93   178.7 1504.29   332.7 1502.22   377.4 1500.49   441.9 1500.48
   456.8 1501.27   466.7 1500.24   481.6 1501.23   501.5 1500.33   536.2 1501.08
   546.2 1500.00   556.1 1497.15     574 1493.97   580.8 1493.60     589 1494.18
   605.6 1497.38   620.4 1502.56   650.1 1499.19   714.4 1497.52   734.2 1498.76
   754.0 1498.48   803.4 1499.93   823.2 1502.17   843.0 1502.50   852.9 1505.36
   872.7 1515.46   882.6 1522.23   902.3 1537.55   917.2 1546.27   927.1 1553.11
#Mann= 3 , 0 , 0
       0     0.1       0     574   0.045       0     589     0.1       0
Bank Sta=     574,     589
Exp/Cntr=0.3,0.1